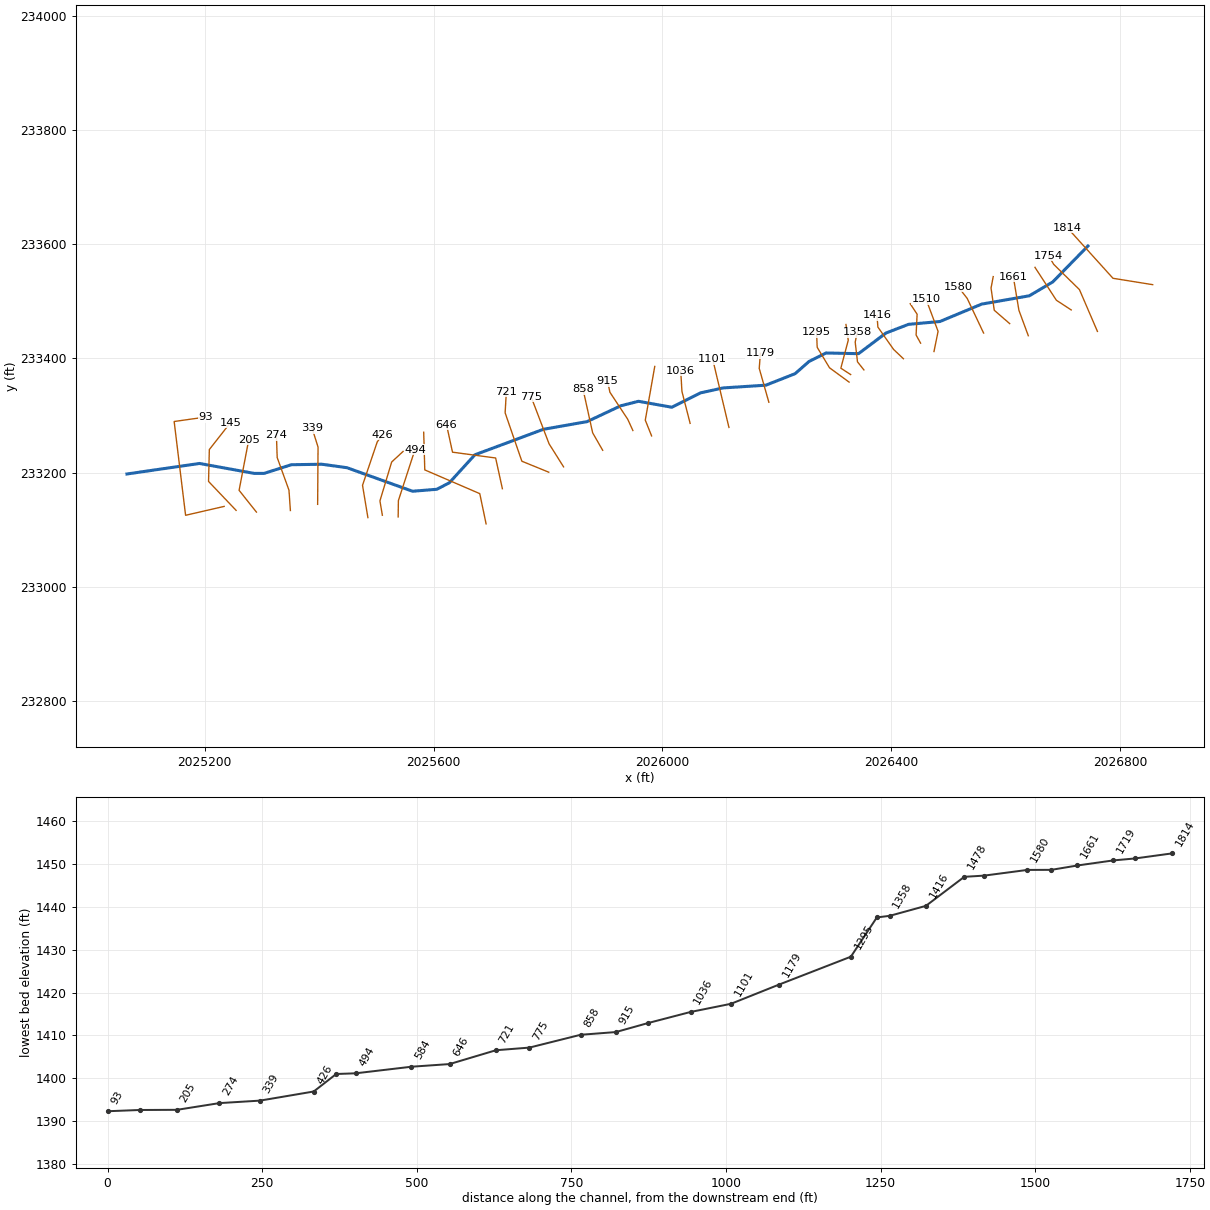
--- HWRDCK.prj (project) ---

Proj Title=HWRDCK
Current Plan=p01
Default Exp/Contr=0,0
English Units
Geom File=g01
Flow File=f01
Plan File=p01
BEGIN DESCRIPTION:
Stream Name: Howard Creek
Flood Zone: Approximate
Summers County, West Virginia
HEC-RAS Version: 5.0.7
Hydrology Method:
regression
Model Notes:
END DESCRIPTION:
DSS Export Rating Curves= 0
DSS Export Rating Curve Sorted= 0
DSS Export Volume Flow Curves= 0
DXF OffsetX= 0
DXF OffsetY= 0
DXF ScaleX= 0
DXF ScaleY= 0

--- HWRDCK.p01 (plan) ---

Plan Title=Floodplain
Program Version=5.07
Short Identifier=Floodplain
Geom File=g01
Flow File=f01
Subcritical Flow
K Sum by GR= 0
Std Step Tol= 0.01
Critical Tol= 0.01
Num of Std Step Trials= 20
Max Error Tol= 0.3
Flow Tol Ratio= 0.001
Split Flow NTrial= 30
Split Flow Tol= 0.02
Split Flow Ratio= 0.02
Log Output Level= 0
Friction Slope Method= 1
Unsteady Friction Slope Method= 2
Unsteady Bridges Friction Slope Method= 1
Parabolic Critical Depth
Global Vel Dist= 0 , 0 , 0
Global Log Level= 0
CheckData=True
Encroach Param=-1 ,0,0, 0
Mapping Interval=1HOUR
Computation Time Step Use Courant=        0
Computation Time Step Use Time Series=    0
Computation Time Step Count To Double=0
Computation Time Step Max Doubling=0
Computation Time Step Max Halving=0
Computation Time Step Residence Courant=0
Run HTab= 0
Run UNet= 0
Run Sediment= 0
Run PostProcess= 0
Run WQNet= 0
Run RASMapper= 0
UNET Theta= 0
UNET Theta Warmup= 0
UNET ZTol= 0
UNET ZSATol= 0
UNET MxIter= 0
UNET Max Iter WO Improvement= 0
UNET MaxInSteps= 0
UNET DtIC= 0
UNET DtMin= 0
UNET MaxCRTS= 0
UNET WFStab= 0
UNET SFStab= 0
UNET WFX= 1
UNET SFX= 1
UNET 1D Methodology=Finite Difference
UNET DSS MLevel= 1
UNET Pardiso=0
UNET DZMax Abort= 0
UNET Use Existing IB Tables= 0
UNET Froude Reduction=False
UNET Froude Limit= 0
UNET Froude Power= 0
UNET D1 Cores= 0
UNET D2 Coriolis=0
UNET D2 Cores= 0
UNET D2 Theta= 1
UNET D2 Theta Warmup= 1
UNET D2 Z Tol= 0.01
UNET D2 Volume Tol= 0.01
UNET D2 Max Iterations= 20
UNET D2 Equation= 0
UNET D2 RampUpFraction=0.1
UNET D2 TimeSlices= 1
UNET D2 BCVolumeCheck=0
UNET D1D2 MaxIter= 0
UNET D1D2 ZTol=0.01
UNET D1D2 QTol=0.1
UNET D1D2 MinQTol=1
Write IC File= 0
Write IC File at Fixed DateTime=0
Write IC File at Sim End=0
Echo Input=False
Echo Parameters=False
Echo Output=False
Write Detailed= 0
HDF Write Warmup=0
HDF Write Time Slices=0
HDF Flush=0
HDF Face Node Velocities=0
HDF Compression= 1
HDF Chunk Size= 1
HDF Spatial Parts= 1
HDF Use Max Rows=0
HDF Fixed Rows= 1
Calibration Method= 0
Calibration Iterations= 20
Calibration Max Change=0.05
Calibration Tolerance=0.2
Calibration Maximum=1.5
Calibration Minimum=0.5
Calibration Optimization Method= 1
WQ AD Non Conservative
WQ ULTIMATE=-1
WQ Max Comp Step=1HOUR
WQ Output Interval=15MIN
WQ Output Selected Increments= 0
WQ Output face flow=0
WQ Output face velocity=0
WQ Output face area=0
WQ Output face dispersion=0
WQ Output cell volume=0
WQ Output cell surface area=0
WQ Output cell continuity=0
WQ Output cumulative cell continuity=0
WQ Output face conc=0
WQ Output face dconc_dx=0
WQ Output face courant=0
WQ Output face peclet=0
WQ Output face adv mass=0
WQ Output face disp mass=0
WQ Output cell mass=0
WQ Output cell source sink temp=0
WQ Output nsm pathways=0
WQ Output nsm derived pathways=0
WQ Output MaxMinRange=-1
WQ Daily Max Min Mean=-1
WQ Daily Range=0
WQ Daily Time=0
WQ Create Restart=0
WQ Fixed Restart=0
WQ System Summary=0
WQ Write To DSS=0
WQ Use Fixed Temperature=0
Sorting and Armoring Iterations= 10
XS Update Threshold= 0.02
Bed Roughness Predictor= 0
Hydraulics Update Threshold= 0.02
Energy Slope Method= 1
Volume Change Method= 1
Sediment Retention Method= 0
XS Weighting Method= 0
Number of US Weighted Cross Sections= 1
Number of DS Weighted Cross Sections= 1
Upstream XS Weight=0
Main XS Weight=1
Downstream XS Weight=0
Number of DS XS's Weighted with US Boundary= 1
Upstream Boundary Weight= 1
Weight of XSs Associated with US Boundary= 0
Number of US XS's Weighted with DS Boundary= 1
Downstream Boundary Weight= 0.5
Weight of XSs Associated with DS Boundary= 0.5
Percentile Method= 0
Sediment Output Level= 3
Mass or Volume Output= 0
Output Increment Type= 1
Profile and TS Output Increment= 1
XS Output Flag= 0
XS Output Increment= 10
Write Gradation File= 0
Read Gradation Hotstart= 0
Write HDF5 File= 1
Write Binary Output= 1
Write DSS Sediment File= 0
SV Curve= 0
Specific Gage Flag= 0

--- HWRDCK.f01 (steady flow) ---

Flow Title=Flows
Program Version=5.07
Number of Profiles= 6
Profile Names=01pct,10pct,04pct,02pct,0_2pct,01plus
River Rch & RM=HWRDCK,Main            ,1814
     438     229     306     370     615     648
River Rch & RM=HWRDCK,Main            ,1510
     533     281     374     451     746     788
Boundary for River Rch & Prof#=HWRDCK,Main            , 1
Up Type= 0
Dn Type= 3
Dn Slope=0.0153
Boundary for River Rch & Prof#=HWRDCK,Main            , 2
Up Type= 0
Dn Type= 3
Dn Slope=0.0153
Boundary for River Rch & Prof#=HWRDCK,Main            , 3
Up Type= 0
Dn Type= 3
Dn Slope=0.0153
Boundary for River Rch & Prof#=HWRDCK,Main            , 4
Up Type= 0
Dn Type= 3
Dn Slope=0.0153
Boundary for River Rch & Prof#=HWRDCK,Main            , 5
Up Type= 0
Dn Type= 3
Dn Slope=0.0153
Boundary for River Rch & Prof#=HWRDCK,Main            , 6
Up Type= 0
Dn Type= 3
Dn Slope=0.0153
DSS Import GetInterval= 0
DSS Import GetPeak= 0
DSS Import FillOption= 0

--- HWRDCK.g01 (geometry) ---

Geom Title=Geometry
Program Version=5.07

River Reach=HWRDCK          ,Main
Reach XY= 30
     2026743.701      233597.003      2026682.31      233534.149
     2026641.338      233509.843     2026558.004       233495.26
     2026485.088      233464.791     2026430.227      233459.843
     2026390.643      233444.565     2026342.726      233408.455
     2026285.869       233409.67     2026256.286      233394.811
     2026231.972      233373.447     2026180.834      233353.246
     2026106.181      233348.472     2026066.685      233339.791
     2026016.338      233314.617     2025958.178      233325.034
     2025927.362      233317.222     2025868.334      233289.444
     2025791.945      233275.989     2025672.154      233231.284
     2025627.449      233182.239     2025605.747      233170.954
     2025563.213      233167.482     2025448.629      233208.715
     2025404.793      233214.791     2025351.407      233213.923
     2025303.665      233198.732     2025286.737      233198.732
     2025190.799      233216.149     2025064.052      233197.731

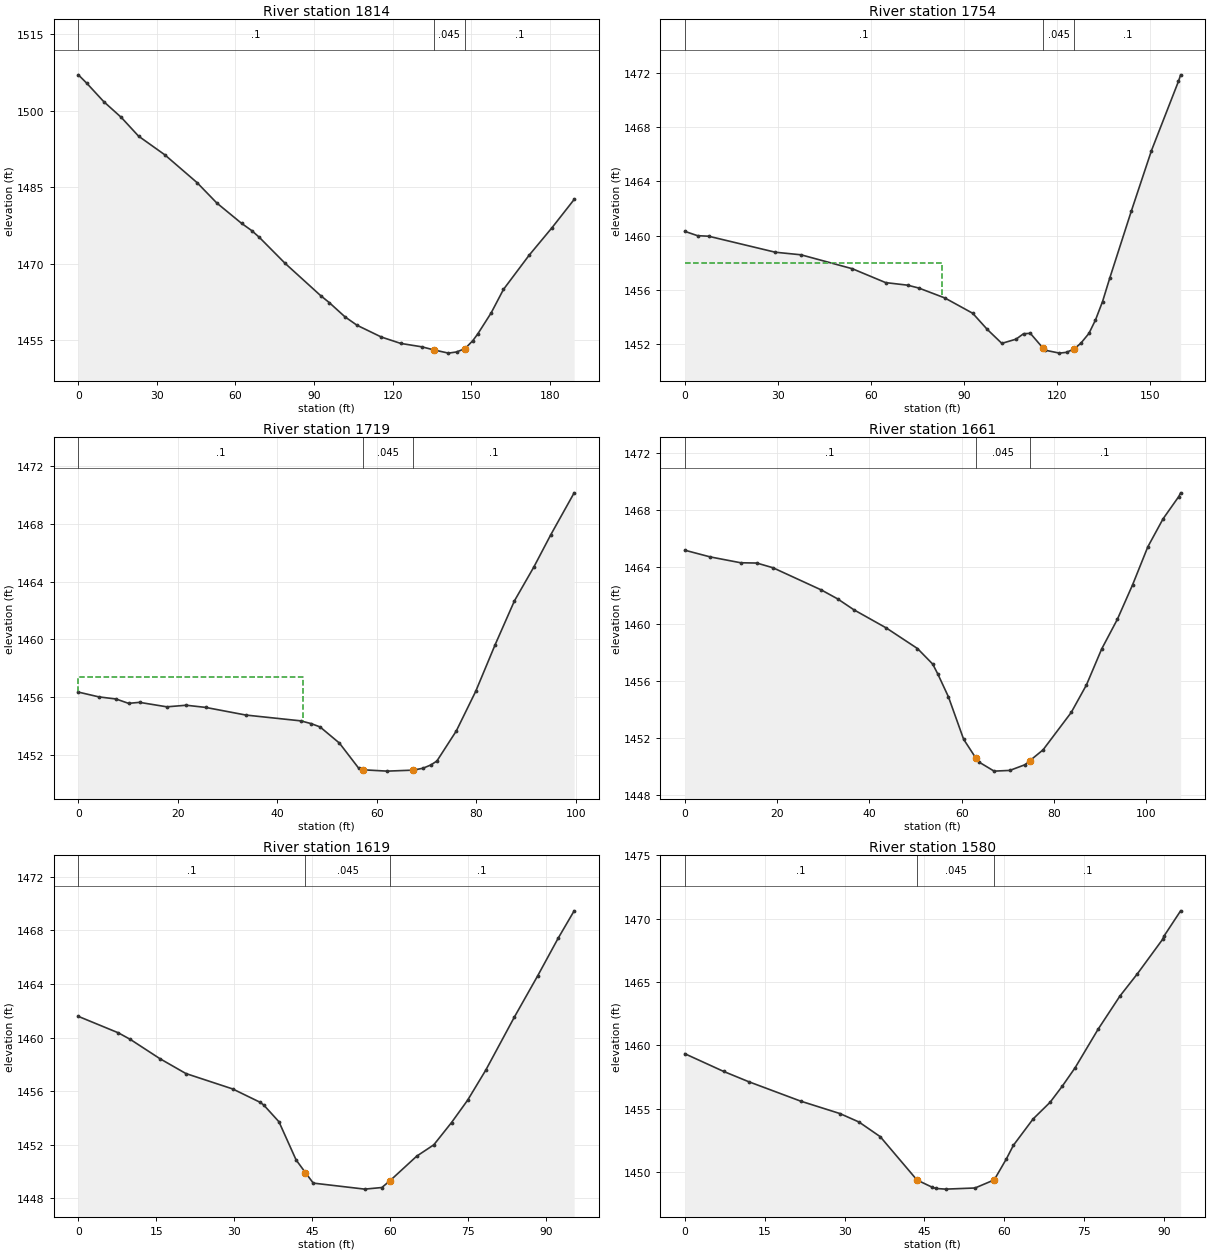
Type RM Length L Ch R = 1 ,1814    ,59.8,59.8,59.8
XS GIS Cut Line= 3
 2026856.8914769233529.3309845772026787.53869327233540.492491695
2026707.80302389233628.920090977
#Sta/Elev= 30
       0 1507.03     3.2  1505.4     9.7 1501.78    16.4 1498.69      23 1495.02
      33 1491.37    45.3 1485.93    52.9 1481.91    62.3 1477.95    66.2 1476.52
    69.1  1475.2      79 1470.08    92.5 1463.79    95.8 1462.42   101.8 1459.63
   106.4 1457.98   115.7 1455.67   123.1 1454.42   131.2 1453.75   135.6 1453.17
   141.3 1452.52   144.4 1452.75   147.6 1453.39   150.6 1454.96   152.5 1456.28
   157.6 1460.39   162.3 1464.99   172.1 1471.69   180.8 1477.06   189.3 1482.62
#Mann= 3 ,-1 , 0
       0      .1       0   135.6    .045       0   147.6      .1       0
Bank Sta=135.6,147.6
XS Rating Curve= 0 ,0
Exp/Cntr(USF)=0,0
Exp/Cntr=0.3,0.1

Type RM Length L Ch R = 1 ,1754    ,37.5,35.3,33.1
XS GIS Cut Line= 4
2026760.33903407233447.4697678342026728.93640798233520.638124088
 2026683.8883286233564.9141959482026675.23366567 233579.80826704
#Sta/Elev= 30
       0 1460.32     4.1    1460     7.7 1459.96    29.2 1458.78    37.5 1458.59
    54.1 1457.56    64.8 1456.54    71.9 1456.35    75.5 1456.14    83.9 1455.41
    92.9 1454.28    97.6 1453.09   102.3 1452.06   106.9 1452.37   109.3 1452.77
   111.5  1452.8   115.71451.684   116.2 1451.56   120.9 1451.34   123.2  1451.4
   125.71451.659   127.8 1452.07   130.4 1452.79   132.5 1453.77   134.8 1455.14
   137.1 1456.85   144.1 1461.82   150.6 1466.28   159.3 1471.38     160 1471.86
#Mann= 3 ,-1 , 0
       0      .1       0   115.7    .045       0   125.7      .1       0
#XS Ineff= 2 , 0
           82.91 1458.01
Permanent Ineff=
       F       F
Bank Sta=115.7,125.7
XS Rating Curve= 0 ,0
Exp/Cntr(USF)=0,0
Exp/Cntr=0.3,0.1

Type RM Length L Ch R = 1 ,1719    ,61.8,57.8,51.9
XS GIS Cut Line= 3
2026714.48721662233485.0710140562026688.59651941233502.043248564
2026651.17410399233559.680884953
#Sta/Elev= 27
       0 1456.35     4.1 1456.02     7.6 1455.87    10.1 1455.57    12.3 1455.64
    17.8 1455.33    21.7 1455.44    25.6 1455.29    33.7 1454.76    44.7 1454.36
    46.8 1454.17    48.6 1453.94    52.5 1452.82    56.4 1451.07    57.31450.971
    62.1 1450.88    67.31450.948    69.3 1451.08    70.9 1451.31    72.1 1451.58
      76 1453.66    79.9  1456.4    83.8 1459.62    87.7 1462.67    91.6 1465.01
      95 1467.24    99.7 1470.14
#Mann= 3 ,-1 , 0
       0      .1       0    57.3    .045       0    67.3      .1       0
#XS Ineff= 2 , 0
           45.16 1457.37
Permanent Ineff=
       F       F
Bank Sta=57.3,67.3
XS Rating Curve= 0 ,0
Exp/Cntr(USF)=0,0
Exp/Cntr=0.3,0.1

Type RM Length L Ch R = 1 ,1661    ,42.5,42.2,41.9
XS GIS Cut Line= 3
2026639.52727014233439.8593448192026623.10886536233484.461406536
2026613.28856762 233543.50785037
#Sta/Elev= 30
       0 1465.18     5.5 1464.71    12.1  1464.3    15.6 1464.28    19.1 1463.95
    29.6 1462.39    33.1 1461.77    36.6 1461.01    43.6 1459.74    50.4 1458.29
    53.7  1457.2    54.8 1456.51    57.1 1454.91    60.4 1451.93      631450.639
    63.7 1450.34      67  1449.7    70.4 1449.75    73.7 1450.15    74.7 1450.42
    77.6 1451.19    83.7 1453.81      87 1455.74    90.3 1458.26    93.7 1460.34
      97 1462.76   100.3 1465.42   103.6 1467.38     107 1468.94   107.4  1469.2
#Mann= 3 ,-1 , 0
       0      .1       0      63    .045       0    74.7      .1       0
Bank Sta=63,74.7
XS Rating Curve= 0 ,0
Exp/Cntr(USF)=0,0
Exp/Cntr=0.3,0.1

Type RM Length L Ch R = 1 ,1619    ,35.8,38.9,43.2
XS GIS Cut Line= 4
2026606.99774871233461.1129070252026580.02740376233484.460369818
2026574.39180929233523.3057173962026578.21596268233543.432840494
#Sta/Elev= 24
       0 1461.58     7.7 1460.35      10 1459.86    15.7 1458.42    20.7 1457.31
    29.7 1456.16      35 1455.16    35.7 1454.95    38.6 1453.71    41.9 1450.86
    43.7 1449.91    45.2 1449.13    55.1 1448.68    58.4  1448.8      60 1449.32
    65.1 1451.14    68.4 1451.99    71.8 1453.65    74.9 1455.32    78.4 1457.57
    83.9 1461.53    88.4 1464.62    92.3  1467.4    95.4 1469.46
#Mann= 3 ,-1 , 0
       0      .1       0    43.7    .045       0      60      .1       0
Bank Sta=43.7,60
XS Rating Curve= 0 ,0
Exp/Cntr(USF)=0,0
Exp/Cntr=0.3,0.1

Type RM Length L Ch R = 1 ,1580    ,70.6,69.8,68.8
XS GIS Cut Line= 3
2026561.36178963233444.6061237192026532.74683581233505.202496516
2026516.75612632233525.822095593
#Sta/Elev= 25
       0 1459.35     7.3 1457.95      12 1457.14    21.8  1455.6    29.1 1454.63
    32.7 1453.96    36.7  1452.8    43.6 1449.38    46.5  1448.8    47.2 1448.71
      49 1448.66    54.5 1448.75    58.1 1449.39    60.4 1451.06    61.7 1452.12
    65.4  1454.2    68.6 1455.52    70.9  1456.8    73.3 1458.25    77.6 1461.28
    81.7  1463.9      85 1465.67    89.7 1468.37      90 1468.65    93.1 1470.63
#Mann= 3 ,-1 , 0
       0      .1       0    43.6    .045       0    58.1      .1       0
Bank Sta=43.6,58.1
XS Rating Curve= 0 ,0
Exp/Cntr(USF)=0,0
Exp/Cntr=0.3,0.1

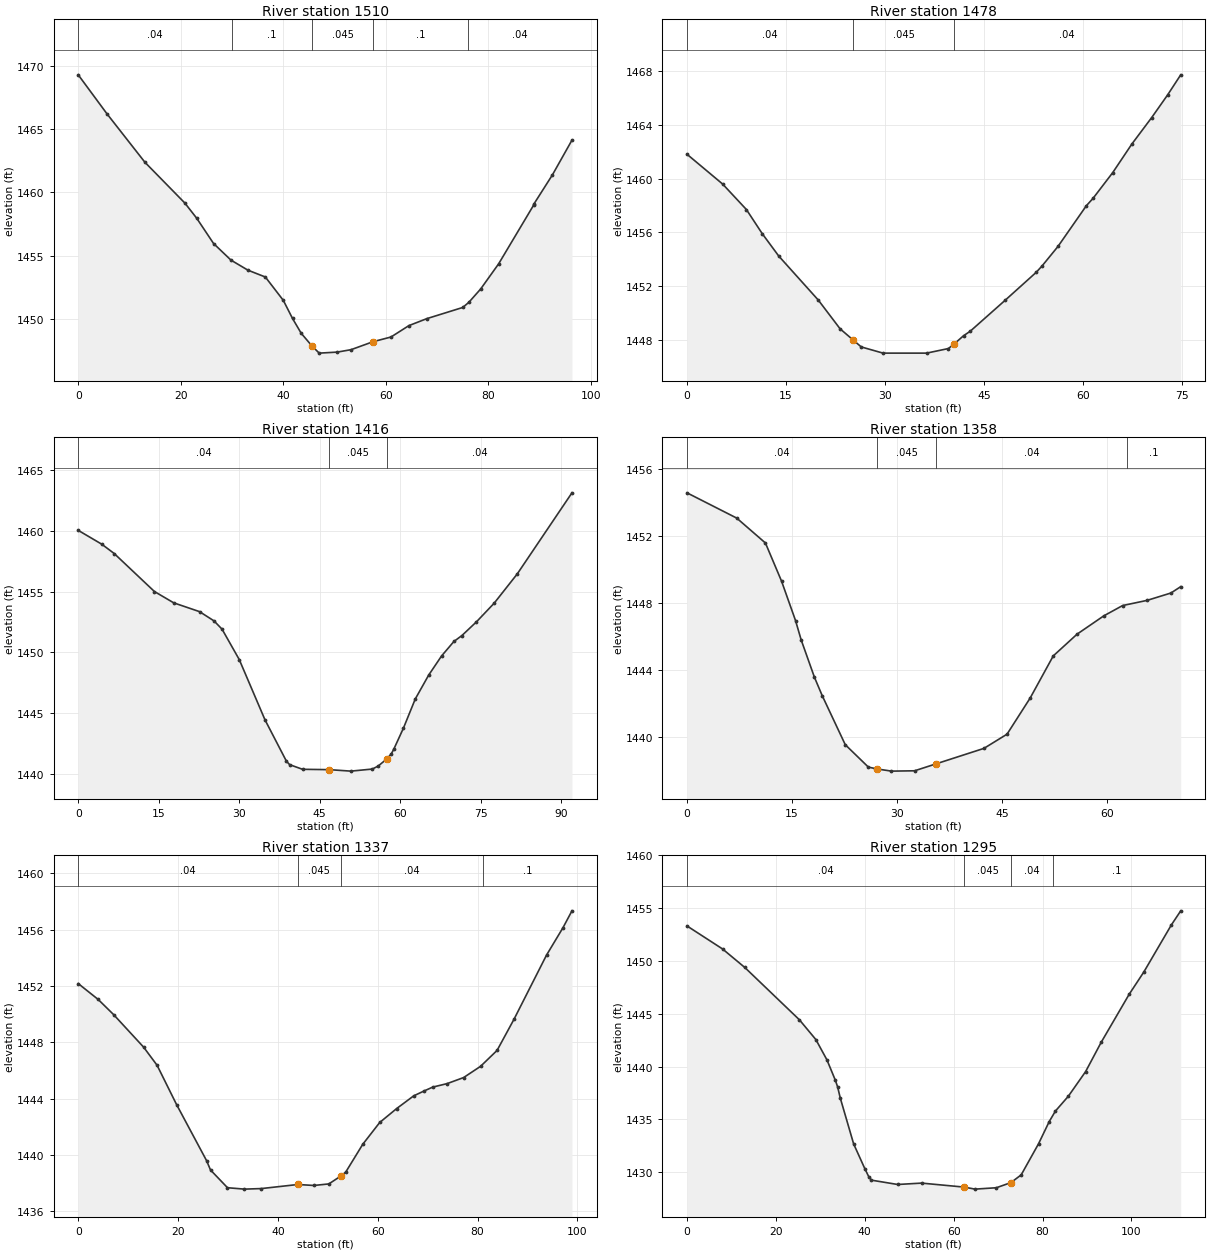
Type RM Length L Ch R = 1 ,1510    ,37.4,32.1,27.9
XS GIS Cut Line= 3
2026474.67531188233412.2038965982026481.82905033 233447.55178073
2026460.78864311233503.940072083
#Sta/Elev= 28
       0 1469.27     5.6  1466.2      13 1462.38    20.8 1459.16    23.1 1457.97
    26.4 1455.97    29.8 1454.66    33.1 1453.87    36.5 1453.33      40 1451.49
    41.8 1450.06    43.5 1448.89    45.6 1447.89      47 1447.33    50.5 1447.41
    53.2  1447.6    57.5 1448.23      61  1448.6    64.5  1449.5      68 1450.05
      75 1450.93    76.2 1451.34    78.5 1452.39      82 1454.37    88.8 1458.98
    88.9  1459.1    92.5 1461.39    96.3 1464.12
#Mann= 5 ,-1 , 0
       0     .04       0      30      .1       0    45.6    .045       0
    57.5      .1       0   76.06     .04       0
Bank Sta=45.6,57.5
XS Rating Curve= 0 ,0
Exp/Cntr(USF)=0,0
Exp/Cntr=0.3,0.1

Type RM Length L Ch R = 1 ,1478    ,52.5,62.1,68
XS GIS Cut Line= 4
  2026451.302174233426.8346049492026443.41878243233441.032680124
2026445.17567901233477.6171479652026433.09940515233495.932829984
#Sta/Elev= 26
       0  1461.8     5.4 1459.59       9  1457.7    11.4 1455.91    13.9 1454.25
    19.9 1450.98    23.2 1448.85    25.21448.012    26.4 1447.51    29.7 1447.05
    36.3 1447.05    39.6 1447.39    40.4  1447.7    41.9 1448.34    42.9 1448.67
    48.2 1450.97    52.9 1453.04    53.8 1453.52    56.2 1454.96    60.5 1457.98
    61.5 1458.52    64.5 1460.44    67.4 1462.56    70.4 1464.52    72.8 1466.19
    74.8 1467.69
#Mann= 3 ,-1 , 0
       0     .04       0    25.2    .045       0    40.4     .04       0
Bank Sta=25.2,40.4
XS Rating Curve= 0 ,0
Exp/Cntr(USF)=0,0
Exp/Cntr=0.3,0.1

Type RM Length L Ch R = 1 ,1416    ,63,58.4,54
XS GIS Cut Line= 4
2026421.23267754233399.5796522652026403.97954362233415.991169898
2026376.62142991233455.0119641822026374.99113294233475.481248372
#Sta/Elev= 30
       0 1460.02     4.4 1458.88     6.7 1458.12    14.2    1455    17.8 1454.07
    22.6 1453.35    25.3 1452.59    26.8 1451.91      30 1449.42    34.8 1444.47
    38.8 1441.07    39.4 1440.79    41.8 1440.41    46.8 1440.38    50.8 1440.26
    54.8 1440.43    55.9 1440.68    57.5 1441.26    58.3 1441.65    58.8 1442.06
    60.6 1443.79    62.8 1446.18    65.3 1448.14    67.7 1449.71      70  1450.9
    71.5 1451.39    74.2 1452.51    77.5 1454.04    81.8 1456.44      92  1463.1
#Mann= 3 ,-1 , 0
       0     .04       0    46.8    .045       0    57.5     .04       0
Bank Sta=46.8,57.5
XS Rating Curve= 0 ,0
Exp/Cntr(USF)=0,0
Exp/Cntr=0.3,0.1

Type RM Length L Ch R = 1 ,1358    ,24.3,20.9,17.4
XS GIS Cut Line= 4
2026352.14803542233380.0588062512026340.97044174233394.129018148
2026336.95857325 233428.787979342026340.54120117233446.057050958
#Sta/Elev= 24
       0 1454.58     7.1 1453.07    11.2 1451.58    13.5  1449.3    15.5 1446.94
    16.3 1445.79    18.2 1443.55    19.3 1442.46    22.6 1439.52    25.9 1438.18
    27.21438.066    29.2 1437.94    32.5 1437.96    35.6 1438.38    42.4  1439.3
    45.7 1440.15      49 1442.31    52.3 1444.83    55.7 1446.13    59.5 1447.22
    62.2 1447.84    65.7 1448.15    69.1 1448.59    70.5 1448.97
#Mann= 4 ,-1 , 0
       0     .04       0    27.2    .045       0    35.6     .04       0
   62.86      .1       0
Bank Sta=27.2,35.6
XS Rating Curve= 0 ,0
Exp/Cntr(USF)=0,0
Exp/Cntr=0.3,0.1

Type RM Length L Ch R = 1 ,1337    ,34,42,49.6
XS GIS Cut Line= 4
2026328.98219991233371.878300417 2026311.8795796233383.012021101
2026324.81548288233431.9285785342026320.79005826233459.502737178
#Sta/Elev= 30
       0 1452.17       4 1451.04     7.1 1449.96    13.1 1447.65    15.8 1446.36
    19.7 1443.57    25.7 1439.59    26.5 1438.92    29.9 1437.66    33.3 1437.56
    36.7  1437.6      441437.889    47.2 1437.82    50.2 1437.93    52.6 1438.49
    53.6 1438.78      57 1440.75    60.4  1442.3    63.8 1443.29    67.2 1444.19
    69.3 1444.54      71 1444.81    73.9 1445.06    77.2 1445.49    80.6 1446.29
    83.9 1447.42    87.3 1449.64    93.8 1454.19    97.1 1456.14    98.9 1457.34
#Mann= 4 ,-1 , 0
       0     .04       0      44    .045       0    52.6     .04       0
   81.01      .1       0
Bank Sta=44,52.6
XS Rating Curve= 0 ,0
Exp/Cntr(USF)=0,0
Exp/Cntr=0.3,0.1

Type RM Length L Ch R = 1 ,1295    ,118.8,116,112.7
XS GIS Cut Line= 4
2026326.28592465233358.6268713052026292.05048893233383.751263649
2026270.51529549233419.643252711 2026269.4109266233446.424198396
#Sta/Elev= 30
       0 1453.31       8 1451.13      13 1449.38    25.3 1444.42      29 1442.55
    31.5 1440.62    33.4 1438.68    33.9 1438.06    34.5    1437    37.5 1432.67
    40.1 1430.25    40.9 1429.57    41.5 1429.24    47.4 1428.83    52.8 1428.96
    62.4 1428.58    64.8 1428.39    69.6 1428.52    72.9 1429.01    75.2 1429.74
    79.1 1432.68    81.5 1434.78    82.9 1435.78    85.8 1437.18    89.7 1439.52
    93.2 1442.29    99.5 1446.84   102.8 1448.95     109 1453.41   111.1 1454.74
#Mann= 4 ,-1 , 0
       0     .04       0    62.4    .045       0    72.9     .04       0
   82.47      .1       0
Bank Sta=62.4,72.9
XS Rating Curve= 0 ,0
Exp/Cntr(USF)=0,0
Exp/Cntr=0.3,0.1

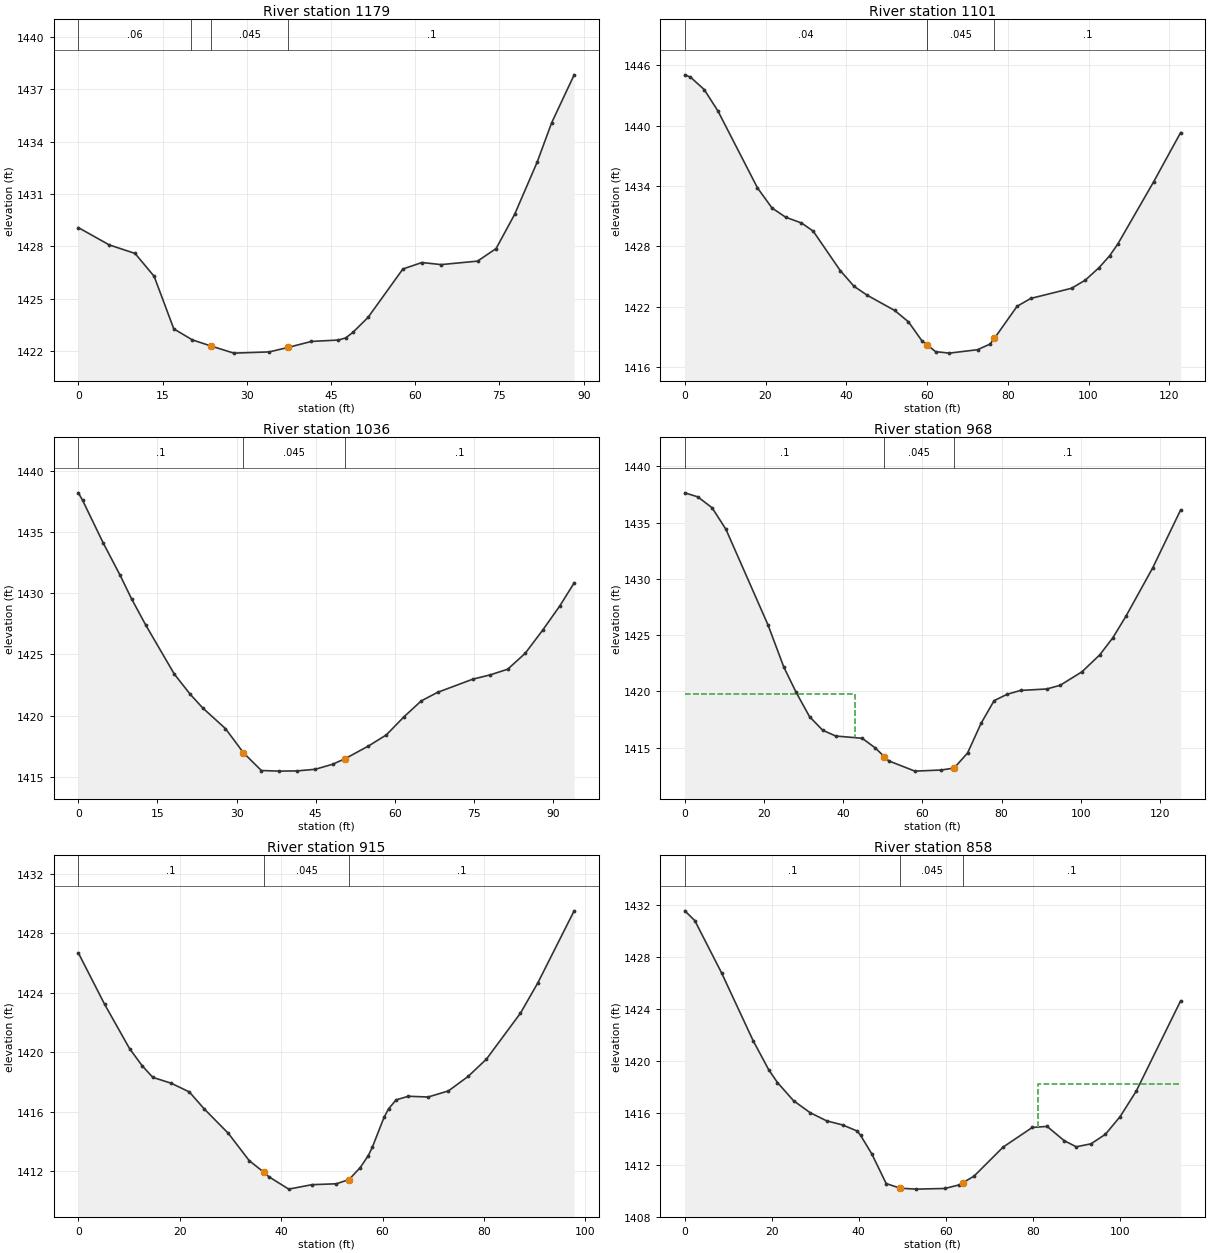
Type RM Length L Ch R = 1 ,1179    ,77.9,77.9,77.3
XS GIS Cut Line= 3
2026186.02913501233323.3994403782026169.19680923233382.733388742
2026171.30084996233409.244301841
#Sta/Elev= 24
       0 1429.07     5.5 1428.08    10.1 1427.59    13.5 1426.28      17 1423.27
    20.3 1422.64    23.7 1422.28    27.7 1421.88      34 1421.95    37.4 1422.21
    41.5 1422.55    46.3 1422.63    47.6 1422.75    48.9 1423.07    51.6 1423.93
    57.8  1426.7    61.2 1427.07    64.6 1426.95    71.1 1427.15    74.4 1427.87
    77.7 1429.83    81.7 1432.81    84.3 1435.08    88.3 1437.82
#Mann= 4 ,-1 , 0
       0     .06       0      20      .1       0    23.7    .045       0
    37.4      .1       0
Bank Sta=23.7,37.4
XS Rating Curve= 0 ,0
Exp/Cntr(USF)=0,0
Exp/Cntr=0.3,0.1

Type RM Length L Ch R = 1 ,1101    ,65.3,65.4,65.6
XS GIS Cut Line= 2
2026116.26527673 233279.248036222026087.87064919233398.759752152
#Sta/Elev= 30
       0 1445.05     1.4 1444.82     4.8 1443.59     8.2 1441.46      18 1433.81
    21.6 1431.81      25 1430.89    28.9 1430.32    31.8 1429.51    38.5 1425.59
    41.9 1424.03    45.2 1423.13      52 1421.62    55.4 1420.49    58.7 1418.62
    60.1 1418.18    62.1 1417.53    65.5 1417.38    72.5 1417.72    75.6 1418.28
    76.71418.862    82.3 1422.04    85.7 1422.82    95.8 1423.83    99.2 1424.64
   102.6 1425.88   105.2 1427.05   107.2  1428.2   116.1  1434.4   122.8 1439.31
#Mann= 4 ,-1 , 0
       0     .04       0      60      .1       0    60.1    .045       0
    76.7      .1       0
Bank Sta=60.1,76.7
XS Rating Curve= 0 ,0
Exp/Cntr(USF)=0,0
Exp/Cntr=0.3,0.1

Type RM Length L Ch R = 1 ,1036    ,73.7,68,62.3
XS GIS Cut Line= 3
2026048.42487178233286.3683236692026034.11739487233342.335806877
2026032.01335415233378.525307298
#Sta/Elev= 29
       0 1438.19      .8 1437.59     4.7 1434.11     7.9 1431.48    10.1 1429.53
    12.8 1427.38    18.2 1423.39    21.2 1421.75    23.6 1420.62    27.9 1418.94
    31.3 1416.97    34.7 1415.52    38.1 1415.47    41.5 1415.49    44.9 1415.62
    48.2 1416.03    50.6 1416.49      55 1417.52    58.4 1418.43    61.7 1419.89
      65  1421.2    68.1  1421.9    74.8 1422.98    78.1 1423.33    81.4 1423.79
    84.7 1425.08      88 1426.96    91.3 1428.97      94 1430.84
#Mann= 3 ,-1 , 0
       0      .1       0    31.3    .045       0    50.6      .1       0
Bank Sta=31.3,50.6
XS Rating Curve= 0 ,0
Exp/Cntr(USF)=0,0
Exp/Cntr=0.3,0.1

Type RM Length L Ch R = 1 ,968     ,39.8,52.7,60.4
XS GIS Cut Line= 3
2025981.07294559233264.415021831 2025970.0541349233291.962048553
2025986.58235093233386.045739819
#Sta/Elev= 30
       0 1437.64     3.3 1437.28     6.9 1436.31    10.4 1434.39      21 1425.91
      25 1422.16    28.1 1419.92    31.5 1417.75    34.8 1416.55    38.1 1416.03
    44.8 1415.83    48.1 1414.97    50.41414.192    51.5 1413.82    58.1 1412.91
    64.8 1413.01      681413.184    71.4 1414.52    74.8 1417.15    78.1 1419.17
    81.4 1419.74    84.8 1420.08    91.4 1420.21    94.8 1420.54   100.3 1421.74
   104.8 1423.25   108.1 1424.77   111.4 1426.68   118.1 1430.94   125.2 1436.12
#Mann= 3 ,-1 , 0
       0      .1       0    50.4    .045       0      68      .1       0
#XS Ineff= 2 , 0
           42.98 1419.72
Permanent Ineff=
       F       F
Bank Sta=50.4,68
XS Rating Curve= 0 ,0
Exp/Cntr(USF)=0,0
Exp/Cntr=0.3,0.1

Type RM Length L Ch R = 1 ,915     ,62.4,57.1,53
XS GIS Cut Line= 4
2025948.36543102233273.8408567932025939.40064372233293.518182272
2025908.19244287233340.9133070262025904.29287272233359.965850237
#Sta/Elev= 30
       0 1426.68     5.2 1423.21    10.1 1420.24    12.6 1419.08    14.7  1418.3
    18.3 1417.91    21.9 1417.32    24.8 1416.19    29.6 1414.53    33.7  1412.7
    36.61411.915    37.6 1411.61    41.5 1410.78    46.1 1411.08    50.9 1411.14
    53.41411.427    55.6 1412.23    57.2 1413.04      58 1413.61    60.3 1415.61
    61.2 1416.19    62.7 1416.79    65.1 1417.03      69 1416.98      73 1417.39
    76.9 1418.37    80.5 1419.53    87.2 1422.62    90.6 1424.64    97.8 1429.51
#Mann= 3 ,-1 , 0
       0      .1       0    36.6    .045       0    53.4      .1       0
Bank Sta=36.6,53.4
XS Rating Curve= 0 ,0
Exp/Cntr(USF)=0,0
Exp/Cntr=0.3,0.1

Type RM Length L Ch R = 1 ,858     ,80.4,82.7,84.7
XS GIS Cut Line= 3
2025895.59637146233239.216540474 2025878.0665201233269.777923904
 2025861.1236747233346.675703279
#Sta/Elev= 30
       0 1431.57     2.3 1430.82     8.5 1426.76    15.7 1421.58    19.3 1419.33
    21.3 1418.35      25 1416.95    28.8 1416.03    32.6  1415.4    36.3 1415.08
    39.6 1414.62    40.4 1414.29      43 1412.85    46.3 1410.57    49.51410.214
    53.1 1410.14    59.8 1410.19    63.1 1410.47      641410.647    66.5 1411.14
    73.2 1413.38    79.9 1414.89    83.3 1414.97    87.2 1413.88      90  1413.4
    93.4 1413.63    96.7 1414.36   100.1 1415.73   103.8 1417.69     114 1424.64
#Mann= 3 ,-1 , 0
       0      .1       0    49.5    .045       0      64      .1       0
#XS Ineff= 2 , 0
                           81.14          1418.2
Permanent Ineff=
       F       F
Bank Sta=49.5,64
XS Rating Curve= 0 ,0
Exp/Cntr(USF)=0,0
Exp/Cntr=0.3,0.1

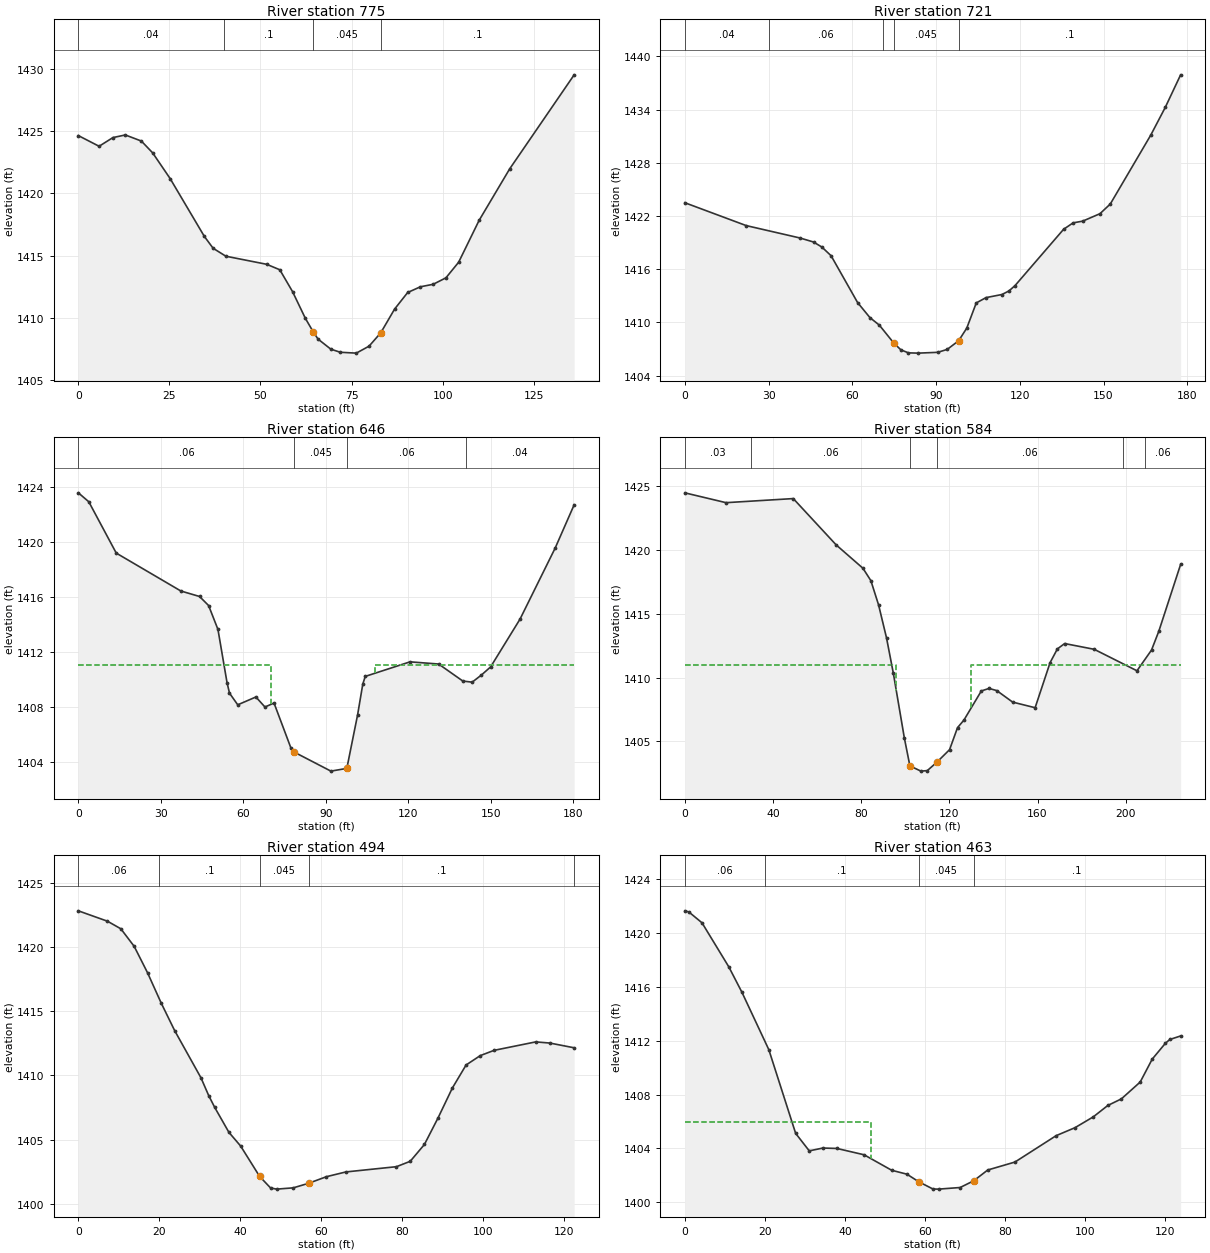
Type RM Length L Ch R = 1 ,775     ,54.9,54.2,53.7
XS GIS Cut Line= 3
2025827.22792241233210.2061193792025801.82532576233250.644307006
2025770.38103046233333.237073925
#Sta/Elev= 30
       0 1424.66     5.7  1423.8     9.5  1424.5    12.9 1424.71    17.3 1424.22
    20.4 1423.27    25.2  1421.2    34.6 1416.54      37 1415.59    40.5 1414.95
    51.7  1414.3    55.3 1413.86    58.8  1412.1    62.3 1409.96    64.51408.849
    65.8 1408.28    69.3 1407.47    71.9 1407.22    76.3 1407.15    79.8 1407.71
      83 1408.78    86.8 1410.69    90.4 1412.03    93.9 1412.49    97.4 1412.69
   100.9 1413.21   104.4 1414.47     110 1417.83   118.4 1421.98   136.1 1429.55
#Mann= 4 ,-1 , 0
       0     .04       0      40      .1       0    64.5    .045       0
      83      .1       0
Bank Sta=64.5,83
XS Rating Curve= 0 ,0
Exp/Cntr(USF)=0,0
Exp/Cntr=0.3,0.1

Type RM Length L Ch R = 1 ,721     ,50.7,74.9,86.1
XS GIS Cut Line= 4
2025801.32300704233200.8436452592025754.28861606233220.084987026
2025725.07028226233304.8894192542025727.20820913233341.946818211
#Sta/Elev= 30
       0 1423.49      22 1420.91    41.3 1419.51    46.1 1419.06    49.1 1418.49
    52.4 1417.51    61.9 1412.23    66.3 1410.54    69.7 1409.68    74.8 1407.69
    77.4  1406.9    80.1 1406.56    83.6 1406.53    90.6 1406.62      94 1406.95
    98.1 1407.93     101 1409.35   104.4 1412.19   107.9 1412.79   113.6 1413.14
   116.1 1413.54   118.3 1414.15   135.7  1420.5   139.1 1421.22   142.5 1421.41
   148.7 1422.25   152.4 1423.34   166.9 1431.11   172.1 1434.24   177.6 1437.91
#Mann= 5 ,-1 , 0
       0     .04       0      30     .06       0   70.82      .1       0
    74.8    .045       0    98.1      .1       0
Bank Sta=74.8,98.1
XS Rating Curve= 0 ,0
Exp/Cntr(USF)=0,0
Exp/Cntr=0.5,0.3

Type RM Length L Ch R = 1 ,646     ,75.1,61.6,58.5
XS GIS Cut Line= 4
2025720.22806601233171.9649130832025708.48794702233225.722300031
 2025633.1040251 233235.917666522025622.59970811233284.113944473
#Sta/Elev= 30
       0 1423.57     3.8 1422.92    13.8 1419.18    37.3 1416.42    44.1 1416.02
    47.4 1415.36    50.8 1413.62    54.1 1409.75      55 1408.98      58 1408.13
    64.6  1408.7    67.9 1407.97    71.2 1408.26    77.3 1405.01    78.6 1404.68
    91.9  1403.3    97.7  1403.5    97.7 1403.51   101.6 1407.39   103.5 1409.64
   104.4  1410.2   120.7 1411.26   131.1  1411.1   139.9 1409.86   143.3 1409.78
   146.6 1410.29     150 1410.89   160.7 1414.37   173.5 1419.55   180.4  1422.7
#Mann= 4 ,-1 , 0
       0     .06       0    78.6    .045       0    97.7     .06       0
  141.09     .04       0
#XS Ineff= 2 , 0
              70    1411     108            1411
Permanent Ineff=
       F       F
Bank Sta=78.6,97.7
XS Rating Curve= 0 ,0
Exp/Cntr(USF)=0,0
Exp/Cntr=0.5,0.3

Type RM Length L Ch R = 1 ,584     ,108.4,90.4,76.2
XS GIS Cut Line= 4
2025691.81707629233110.2791326612025680.75588556233163.296564091
2025584.63795232 233204.871384422025582.73085047 233270.85710843
#Sta/Elev= 30
       0 1424.45    18.7 1423.68    49.2    1424    68.7 1420.37    80.8 1418.55
    84.4 1417.58    87.9 1415.68    91.5  1413.1    94.6 1410.33    99.6 1405.26
   102.1 1403.09   107.1 1402.68     110 1402.72   114.41403.389   120.1 1404.36
   123.7 1406.08   126.6 1406.67   134.5 1408.95     138 1409.15   141.5 1408.98
   148.7 1408.08   158.9 1407.64   165.7 1411.17     169 1412.24   172.3 1412.66
   185.7 1412.21   205.1 1410.53   211.7 1412.15     215 1413.62   224.9 1418.85
#Mann= 6 ,-1 , 0
       0     .03       0      30     .06       0   102.1    .045       0
   114.4     .06       0  198.88     .04       0  208.88     .06       0
#XS Ineff= 2 , 0
              96    1411     130            1411
Permanent Ineff=
       F       F
Bank Sta=102.1,114.4
XS Rating Curve= 0 ,0
Exp/Cntr(USF)=0,0
Exp/Cntr=0.5,0.3

Type RM Length L Ch R = 1 ,494     ,31.8,31.3,32.7
XS GIS Cut Line= 3
2025538.10466718233122.4845845012025538.48608755233151.091112251
2025567.47403567 233240.34347883
#Sta/Elev= 30
       0 1422.84     7.2 1422.03    10.5 1421.44    13.8 1420.07    17.1 1418.01
    20.5 1415.63    23.8  1413.5    30.3 1409.82    32.2 1408.44    33.7 1407.51
    37.2 1405.57    40.1  1404.5    44.81402.128    47.5 1401.23      49 1401.14
    53.1 1401.24    56.91401.597    61.3 1402.11    66.1 1402.48    78.6 1402.89
      82 1403.31    85.5 1404.62    88.9 1406.71    92.4 1409.02    95.8 1410.82
    99.3 1411.55   102.7 1411.96     113 1412.62   116.5 1412.53   122.5 1412.16
#Mann= 5 ,-1 , 0
       0     .06       0      20      .1       0    44.8    .045       0
    56.9      .1       0  122.45     .06       0
Bank Sta=44.8,56.9
XS Rating Curve= 0 ,0
Exp/Cntr(USF)=0,0
Exp/Cntr=0.5,0.3

Type RM Length L Ch R = 1 ,463     ,36.8,36.4,35.8
XS GIS Cut Line= 4
2025510.48256651233125.4270734762025506.23270945 233150.60806162
2025526.73805213233218.6632604612025546.71447039233237.234928028
#Sta/Elev= 30
       0 1421.64       1 1421.56     4.3 1420.75      11 1417.48    14.3 1415.58
      21 1411.33    27.7 1405.12    31.1 1403.82    34.5 1404.03      38    1404
    44.8 1403.53    51.7 1402.38    55.5 1402.09    58.5 1401.52      62 1400.99
    63.4 1400.98    68.8  1401.1    72.2  1401.6    75.7  1402.4    82.5 1402.99
    92.8 1404.95    97.5 1405.54   102.1 1406.35   105.7 1407.19   109.1 1407.68
   113.8 1408.93   116.8 1410.63   120.1 1411.81   121.2 1412.09   123.9 1412.35
#Mann= 4 ,-1 , 0
       0     .06       0      20      .1       0    58.5    .045       0
    72.2      .1       0
#XS Ineff= 2 , 0
            46.5    1406
Permanent Ineff=
       F       F
Bank Sta=58.5,72.2
XS Rating Curve= 0 ,0
Exp/Cntr(USF)=0,0
Exp/Cntr=0.5,0.3

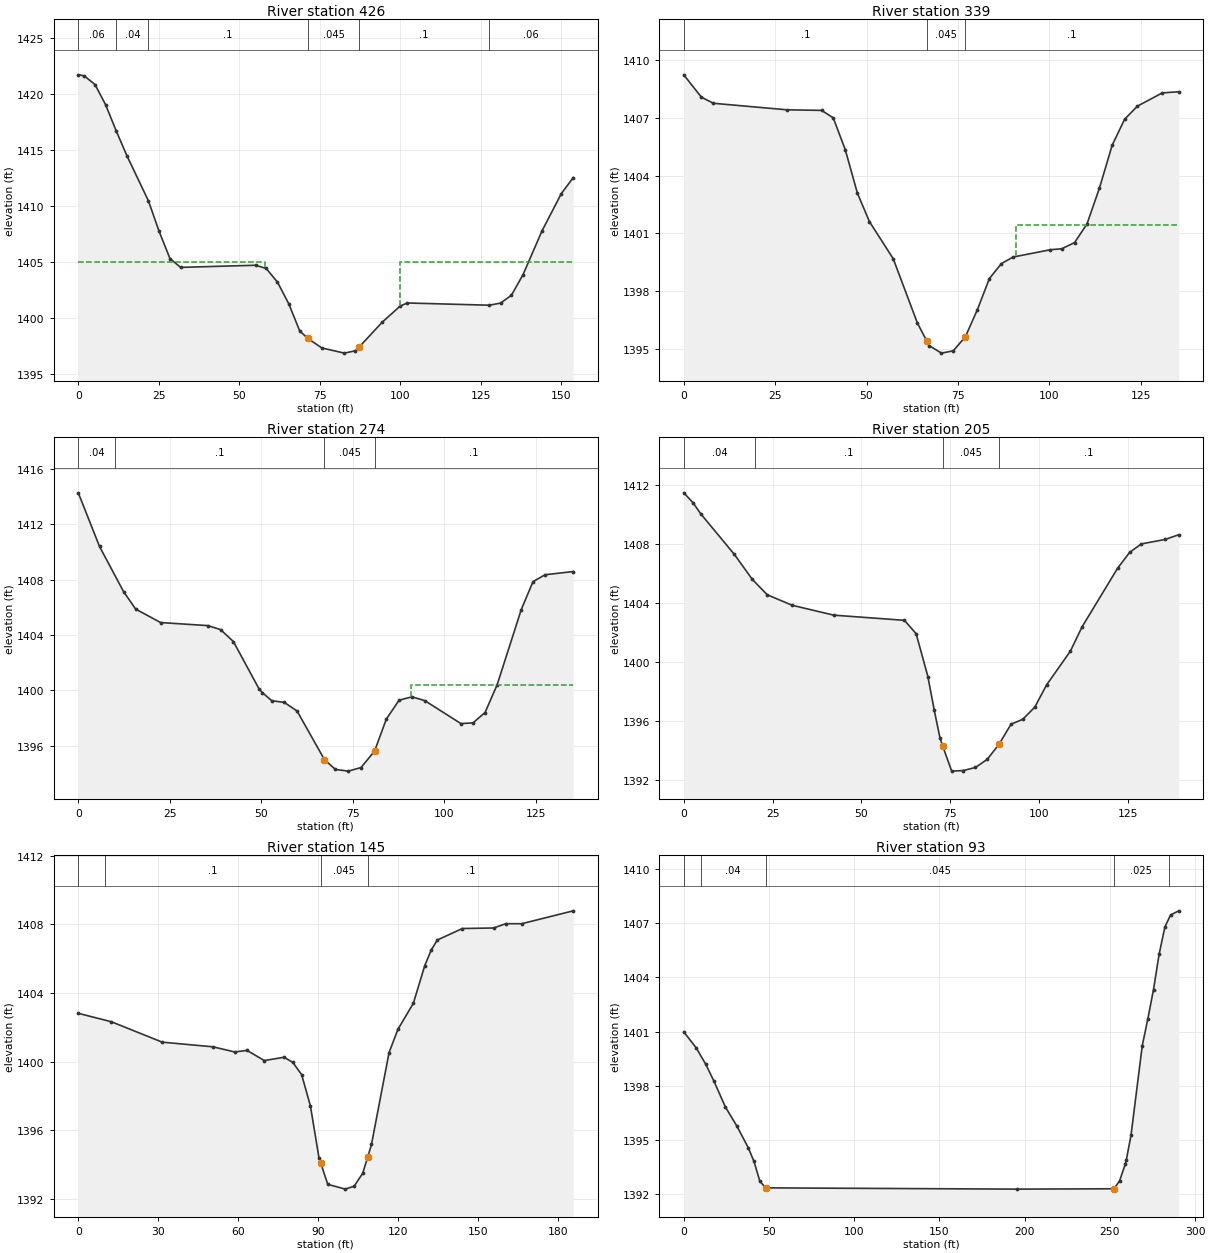
Type RM Length L Ch R = 1 ,426     ,83.6,86.9,90.6
XS GIS Cut Line= 4
2025485.20143724233121.3174003642025475.81430164233177.916306193
2025501.56884027233254.008885648  2025511.259159233266.872354199
#Sta/Elev= 30
       0 1421.75     1.8 1421.67     5.2 1420.88     8.5 1419.07    11.8 1416.73
    15.1 1414.53    21.8 1410.49    25.1 1407.78    28.5 1405.33    31.8 1404.55
    55.1 1404.74    58.4 1404.45    61.9 1403.23    65.4  1401.3    68.8 1398.88
    71.31398.208    75.7 1397.35    82.7 1396.89    86.1  1397.1    87.31397.442
    94.4 1399.64     100 1401.09   102.2 1401.37   127.7 1401.17   131.2 1401.36
   134.6 1402.06   138.2  1403.9   144.1 1407.81   150.1 1411.14   153.8 1412.57
#Mann= 6 ,-1 , 0
       0     .06       0    11.8     .04       0    21.8      .1       0
    71.3    .045       0    87.3      .1       0   127.7     .06       0
#XS Ineff= 2 , 0
              58    1405     100            1405
Permanent Ineff=
       F       F
Bank Sta=71.3,87.3
XS Rating Curve= 0 ,0
Exp/Cntr(USF)=0,0
Exp/Cntr=0.5,0.3

Type RM Length L Ch R = 1 ,339     ,61,65.5,68.8
XS GIS Cut Line= 3
2025397.36094718233144.538855159 2025398.0755937233244.870374679
2025387.50910119233278.274125184
#Sta/Elev= 30
       0 1409.24     4.8 1408.08     8.1 1407.76    28.2 1407.42    37.7 1407.39
    40.9    1407    44.2 1405.33    47.5 1403.08    50.8  1401.6    57.3 1399.67
    63.9 1396.33    66.5 1395.38    67.2 1395.14    70.5 1394.76    73.7 1394.88
      77  1395.6    80.3 1397.01    83.6 1398.64    86.9 1399.42    90.1 1399.76
   100.3 1400.14   103.4 1400.19   106.9 1400.51   110.3 1401.48   113.7 1403.34
   117.2 1405.58   120.6 1406.93   124.1 1407.61   130.9  1408.3   135.4 1408.36
#Mann= 3 ,-1 , 0
       0      .1       0    66.5    .045       0      77      .1       0
#XS Ineff= 2 , 0
                           90.93         1401.43
Permanent Ineff=
       F       F
Bank Sta=66.5,77
XS Rating Curve= 0 ,0
Exp/Cntr(USF)=0,0
Exp/Cntr=0.3,0.1

Type RM Length L Ch R = 1 ,274     ,76.2,68.7,63.1
XS GIS Cut Line= 4
2025349.72877767233133.7242743272025347.25877364 233169.27719569
 2025326.6495129233226.5150137772025325.31472631233265.286542475
#Sta/Elev= 30
       0 1414.26     5.8 1410.39    12.4 1407.12    15.7 1405.87    22.5  1404.9
    35.4 1404.68    38.9 1404.39    42.4 1403.53    49.4 1400.12    50.3 1399.85
    52.9 1399.26    56.3 1399.14    59.8 1398.52    67.31395.007    70.3  1394.3
    73.8 1394.18    77.3 1394.44      81 1395.63    84.2 1397.93    87.7  1399.3
    91.2 1399.54    94.7 1399.27   104.6 1397.61   107.9 1397.66   111.2 1398.41
   114.5 1400.41   121.1 1405.84   124.3 1407.85   127.6 1408.35   135.3 1408.58
#Mann= 4 ,-1 , 0
       0     .04       0      10      .1       0    67.3    .045       0
      81      .1       0
#XS Ineff= 2 , 0
                           90.94          1400.4
Permanent Ineff=
       F       F
Bank Sta=67.3,81
XS Rating Curve= 0 ,0
Exp/Cntr(USF)=0,0
Exp/Cntr=0.3,0.1

Type RM Length L Ch R = 1 ,205     ,62.7,60.5,64.1
XS GIS Cut Line= 3
  2025290.368295233130.9844811822025260.06025098233169.078077795
2025277.02163341233258.055821708
#Sta/Elev= 30
       0 1411.47     2.6  1410.8     4.8 1410.04    14.2 1407.31    19.3  1405.6
    23.5 1404.56    30.5 1403.85    42.2 1403.18    62.1 1402.83    65.4 1401.92
    68.7 1399.02    70.5 1396.73    72.1 1394.86    72.91394.287    75.4 1392.61
    78.7 1392.65    82.1 1392.86    85.4 1393.41    88.7 1394.42    92.1 1395.79
    95.4 1396.12    98.8 1396.95   102.1 1398.45   108.8 1400.74   112.1 1402.39
   122.1 1406.36   125.5 1407.44   128.8 1408.01   135.5 1408.31   139.3 1408.63
#Mann= 4 ,-1 , 0
       0     .04       0      20      .1       0    72.9    .045       0
    88.7      .1       0
Bank Sta=72.9,88.7
XS Rating Curve= 0 ,0
Exp/Cntr(USF)=0,0
Exp/Cntr=0.3,0.1

Type RM Length L Ch R = 1 ,145     ,64.2,51.7,73
XS GIS Cut Line= 4
2025254.77719743233134.0430911292025206.67360463 233184.64918298
2025208.06388188233240.5383283752025245.04525669233287.807754829
#Sta/Elev= 30
       0 1402.81    12.4 1402.32    31.5 1401.13    50.5 1400.86    58.7 1400.56
    63.3 1400.65    69.8 1400.06    77.2 1400.25    80.5 1399.95    83.8 1399.24
    87.1 1397.41    90.3  1394.4      911394.071    93.6 1392.85   100.2 1392.57
   103.5 1392.74   106.7 1393.49   108.61394.441     110 1395.17   116.6 1400.52
   119.9 1401.87   125.7 1403.39     130 1405.59   132.4 1406.49   134.7 1407.08
   144.1 1407.75   155.8 1407.78   160.4 1408.03   166.4 1408.03   185.7 1408.78
#Mann= 4 ,-1 , 0
       0     .04       0      10      .1       0      91    .045       0
   108.6      .1       0
Bank Sta=91,108.6
XS Rating Curve= 0 ,0
Exp/Cntr(USF)=0,0
Exp/Cntr=0.3,0.1

Type RM Length L Ch R = 1 ,93      ,,,
XS GIS Cut Line= 4
2025233.90895636233140.9105887332025166.54449893233125.361483728
2025146.56155734233289.6274945252025201.78000205233297.467150256
#Sta/Elev= 23
       0 1400.99     7.3  1400.1    12.8 1399.21    17.7 1398.26    24.4 1396.83
    31.1 1395.78    37.9 1394.56    41.2 1393.81    44.6 1392.73      48 1392.35
   195.6 1392.28   252.4  1392.3   255.7 1392.74   259.1 1393.68   259.7 1393.92
   262.4 1395.26     269 1400.22   272.3 1401.72   275.6 1403.33   278.9 1405.29
   282.3  1406.8   285.6 1407.46   290.4 1407.69
#Mann= 5 ,-1 , 0
       0      .1       0      10     .04       0      48    .045       0
   252.4    .025       0  284.61      .1       0
Bank Sta=48,252.4
XS Rating Curve= 0 ,0
Exp/Cntr(USF)=0,0
Exp/Cntr=0.3,0.1
LCMann Table=0

Chan Stop Cuts=-1
Use User Specified Reach Order=0
Composite Channel Slope=5